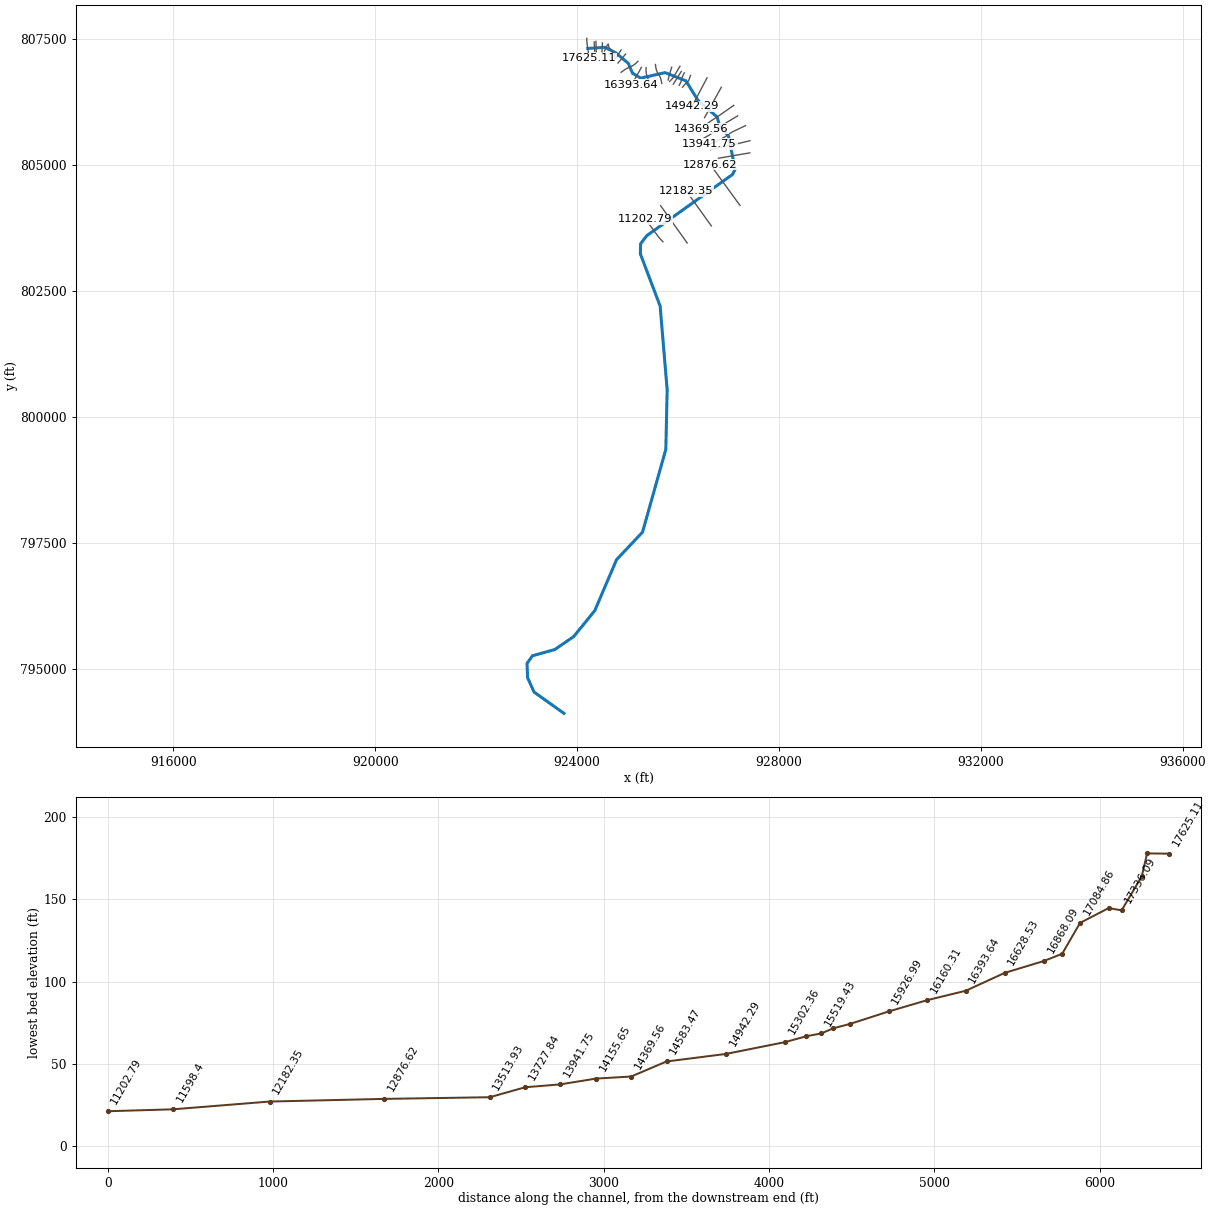
--- 13270_ras.prj (project) ---

Proj Title=13270
Current Plan=p01
Default Exp/Contr=0.3,0.1
English Units
Geom File=g01
Flow File=f01
Plan File=p01
Y Axis Title=Elevation
X Axis Title(PF)=Main Channel Distance
X Axis Title(XS)=Station
BEGIN DESCRIPTION:
RFD model 13270 exported to HEC-RAS
END DESCRIPTION:

--- 13270_ras.p01 (plan) ---

Plan Title=Plan 01
Program Version=4.10
Short Identifier=Plan 01
Geom File=g01
Flow File=f01
Subcritical Flow
Calc Critical at every XS
Secant Critical Depth

--- 13270_ras.f01 (steady flow) ---

Flow Title=Flow 01
Program Version=5.01
Number of Profiles= 6
Profile Names=10yr,25yr,50yr,100yr,100plus,500yr
River Rch & RM=13270,42,17625.11
  175.42  281.68  381.16  472.42  689.73 1197.01
River Rch & RM=13270,42,17257.53
  180.33  289.87  392.51  486.78  710.71  1229.8
River Rch & RM=13270,42,17084.86
  235.85  381.79  519.49  646.87  944.43 1583.63
River Rch & RM=13270,42,16976.69
  237.17  383.99  522.55  650.73  950.06 1592.06
River Rch & RM=13270,42,16868.09
  239.48  387.84  527.88  657.47  959.91 1606.77
River Rch & RM=13270,42,16628.53
  249.49  404.58  551.16  686.99 1003.01 1671.29
River Rch & RM=13270,42,16393.64
  255.87  415.27  566.04  705.87 1030.57  1712.4
River Rch & RM=13270,42,16160.31
   262.6  426.67     582  726.23  1060.3 1757.17
River Rch & RM=13270,42,15926.99
     268  435.99  595.22  743.28 1085.19 1795.49
River Rch & RM=13270,42,15693.66
  270.81  440.85  602.12   752.2 1098.21 1815.53
River Rch & RM=13270,42,15592.61
  277.24  451.98  617.94  772.61 1128.01 1861.28
River Rch & RM=13270,42,15429.66
  278.09  453.44     620  775.27  1131.9 1867.22
River Rch & RM=13270,42,15302.36
  279.74  456.31  624.08  780.56 1139.61 1879.07
River Rch & RM=13270,42,14942.29
  289.75  473.75  648.96  812.79 1186.68 1951.51
River Rch & RM=13270,42,14583.47
  303.69  498.03  683.58  857.66 1252.18 2051.57
River Rch & RM=13270,42,14369.56
  308.14  505.82  694.71  872.12  1273.3 2083.86
River Rch & RM=13270,42,14155.65
  310.92  510.74  701.78  881.35 1286.77 2104.65
River Rch & RM=13270,42,13941.75
  421.51  703.12  976.15 1236.99 1806.01 2872.03
River Rch & RM=13270,42,13727.84
  426.51  712.02  989.03 1253.89 1830.68 2908.68
River Rch & RM=13270,42,13513.93
  430.61  719.31  999.57 1267.71 1850.86 2938.52
River Rch & RM=13270,42,12876.62
  448.67  752.05 1047.42 1331.08 1943.37 3077.89
River Rch & RM=13270,42,12182.35
  467.14  784.68 1094.44 1392.56 2033.14 3208.44
River Rch & RM=13270,42, 11598.4
  618.81 1039.01 1449.14 1843.04 2690.83 4075.89
River Rch & RM=13270,42,11202.79
  636.44 1069.57 1492.67 1899.37 2773.08 4187.35
River Rch & RM=13270,42,11003.82
  637.65 1071.74 1495.84 1903.55 2779.18 4195.98
River Rch & RM=13270,42,10523.64
   735.7 1238.47 1730.52 2204.01 3217.85  4766.7
River Rch & RM=13270,42,10381.57
  736.29 1239.53 1732.06 2206.04 3220.81 4770.81
River Rch & RM=13270,42,10206.82
   741.1 1248.12 1744.51 2222.41 3244.71  4803.6
River Rch & RM=13270,42,9777.784
  770.09 1299.47 1818.67 2319.52  3386.5 4995.83
River Rch & RM=13270,42,8953.241
 1098.54 1900.95  2705.4 3501.93 5112.82 7353.01
River Rch & RM=13270,42,7923.425
 1109.82 1921.46 2735.55 3542.03 5171.36 7430.18
River Rch & RM=13270,42,6525.263
 1156.12 2006.58 2861.45 3710.42 5417.21 7757.29
River Rch & RM=13270,42,5445.107
 1192.12 2072.83 2959.51 3841.65 5608.81  8011.1
River Rch & RM=13270,42,    4281
 1216.88  2118.6 3027.46 3932.83 5741.94 8187.79
Boundary for River Rch & Prof#=13270,42,1
Up Type= 0
Dn Type= 2
Boundary for River Rch & Prof#=13270,42,2
Up Type= 0
Dn Type= 2
Boundary for River Rch & Prof#=13270,42,2
Up Type= 0
Dn Type= 2
Boundary for River Rch & Prof#=13270,42,2
Up Type= 0
Dn Type= 2
Boundary for River Rch & Prof#=13270,42,2
Up Type= 0
Dn Type= 2
Boundary for River Rch & Prof#=13270,42,2
Up Type= 0
Dn Type= 2

--- 13270_ras.g01 (geometry) ---

Geom Title=13270
Program Version=4.10

River Reach=13270,42
Reach XY= 30
924210.038201894807307.023790801924551.797047648807328.887635474
924765.984622383807219.234854333925013.114255637807011.752801105
  925097.0805721 806815.50517644925259.262325409806718.644579901
925742.202038561806827.452684766926153.679057869 806665.58875239
926397.283158752806273.332079917926775.652804376805946.662693892
926816.553992096 805786.35291324926997.977603202 805571.94319101
927130.790103169804910.484857693927076.970658753804808.054302159
925380.358563963803597.344652891925257.526214305803436.960552158
 925252.31788099803236.439718815925644.588648788 802200.84995234
 925783.66014806 800542.51089028925757.266463815799362.499115863
925294.963786666797720.129171912924781.074897763797176.726394185
924349.477675531796165.702088576923930.640870007795651.379171912
923557.376981116795395.302783006923114.668647738795271.604866381
923006.161703292795119.695144133923019.182536633794833.236810799
923147.220731111794551.118755264923739.668647773794130.111810815

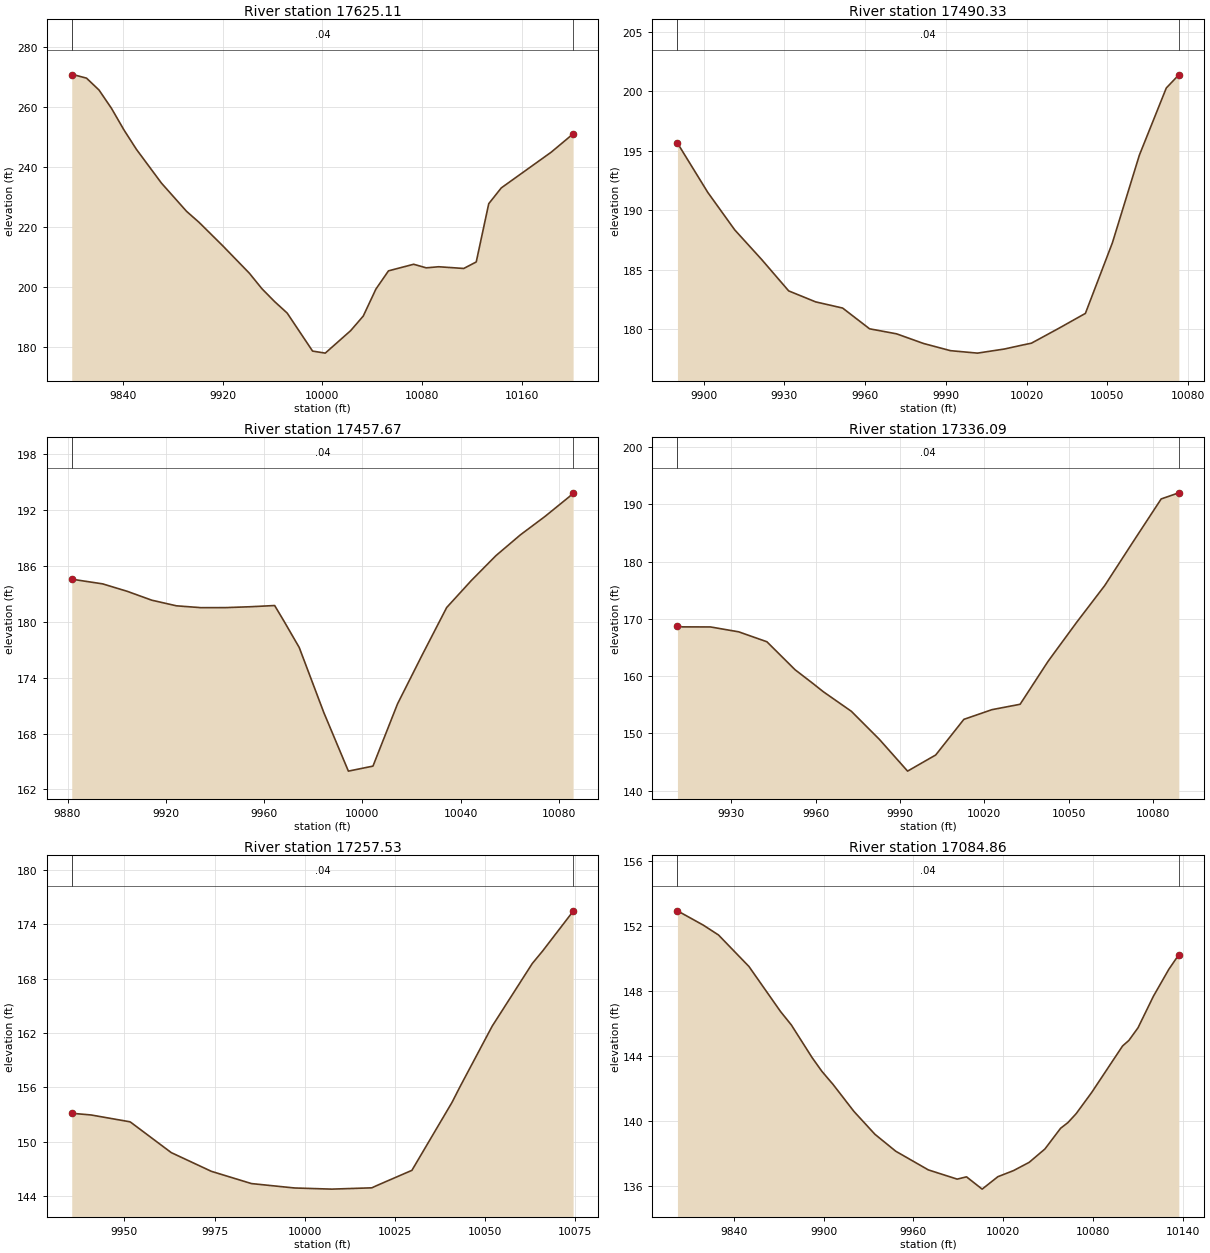
Type RM Length L Ch R = 1 ,17625.11,134.779200,134.779200,134.779200
XS GIS Cut Line= 6
924190.103104882807506.843789609924192.602792622807446.377324043
924198.216611427807386.144247523924224.030931287807220.357880485
924227.558238595807167.446744089924227.759617524807107.366257173
#Sta/Elev= 30
9799.018 270.8139800.864270.86389810.872 269.7529820.881265.78589830.889259.6526
9840.898 252.4359850.906245.93679870.963234.6548 9891.05225.23459901.093221.5463
9920.031213.73139941.395204.55099951.499199.35249961.603195.07339971.748191.2088
9992.087178.508410002.26177.823410022.58185.319310032.74190.223810042.86199.2299
10052.94205.3289 10073.1 207.53210083.18206.338710093.23206.699310113.28206.1279
 10123.3208.304710133.32227.775710143.34 233.04810183.34244.983710200.97251.1215
#Mann= 3 , 0 , 0
9799.018    0.04       09799.018    0.04       010200.97    0.04       0
#XS Ineff= 2 , 0
       0                               0
Bank Sta=9799.018,10200.97
Exp/Cntr=0.3,0.1

Type RM Length L Ch R = 1 ,17490.33,32.657400,32.657400,32.657400
XS GIS Cut Line= 2
924336.420853432807436.238849027924348.888973085807250.350519649
#Sta/Elev= 22
9890.227195.66139891.469195.17979901.491191.49589911.514188.34289921.536185.8493
9931.559183.21619941.581182.29369951.604181.77419961.626180.03039971.648179.6088
9981.671178.79729991.693178.193310001.72177.987210011.74178.333110018.42178.6665
10021.76178.823210031.78180.053410041.81181.325310051.83187.250210061.85194.6126
10071.87200.265110076.53201.3714
#Mann= 3 , 0 , 0
9890.227    0.04       09890.227    0.04       010076.53    0.04       0
#XS Ineff= 2 , 0
       0    9973        10019.05       0
Bank Sta=9890.227,10076.53
Exp/Cntr=0.3,0.1

Type RM Length L Ch R = 1 ,17457.67,121.580000,121.580000,121.580000
XS GIS Cut Line= 2
924372.123757388807447.573503257924378.924549926807243.549727111
#Sta/Elev= 24
9881.716184.60869884.291184.49449894.297184.09479904.302183.29479914.308  182.34
9924.313181.73719934.319181.53669944.324181.5421 9954.33181.63499964.336181.7662
9968.051180.12179974.341177.25549984.347170.26399994.352 163.96910004.36 164.508
10014.36171.197510024.37176.438410034.37181.552110044.38184.446610054.39187.1203
10064.39189.3631 10074.4191.3421 10084.4193.484210085.85193.8793
#Mann= 3 , 0 , 0
9881.716    0.04       09881.716    0.04       010085.85    0.04       0
#XS Ineff= 2 , 0
       0                               0
Bank Sta=9881.716,10085.85
Exp/Cntr=0.3,0.1

Type RM Length L Ch R = 1 ,17336.09,78.563400,78.563400,78.563400
XS GIS Cut Line= 6
924501.143107275807416.734743791924497.753030424807368.772467152
 924496.57576162807328.689824576924496.536553472807326.690208932
 924495.26912239 807286.18582527924490.836444414807238.742358094
#Sta/Elev= 25
9910.818168.80899912.557168.62439922.582168.60879932.607167.75629942.632166.0245
9952.657161.1362  9958.9 158.7789962.674157.30619972.678153.87719982.683148.9552
9992.687143.4259    9999145.2096   10001145.772710002.69146.2478 10012.7152.4679
 10022.7154.163810032.71155.102310041.52161.751810042.72162.644610044.42163.7926
10052.76169.3779 10062.8175.833310072.85183.443110082.89190.968910089.17 192.036
#Mann= 3 , 0 , 0
9910.818    0.04       09910.818    0.04       010089.17    0.04       0
#XS Ineff= 2 , 0
       0                               0
Bank Sta=9910.818,10089.17
Exp/Cntr=0.3,0.1

Type RM Length L Ch R = 1 ,17257.53,172.664100,172.664100,172.664100
XS GIS Cut Line= 2
924602.046884241807379.808424572924541.282995352807254.808424572
#Sta/Elev= 21
9935.423153.1458 9940.77 152.9599951.542152.20659951.889152.11929963.008148.8053
9974.127 146.7399974.415146.70349985.246145.38579996.365144.93329997.288144.8995
10007.48144.7742 10018.6144.917510020.16145.199310029.72146.846910040.84154.3487
10043.03156.056410051.96 162.75110063.08169.669110065.91171.0308 10074.2175.3296
10074.41175.4882
#Mann= 3 , 0 , 0
9935.423    0.04       09935.423    0.04       010074.41    0.04       0
#XS Ineff= 2 , 0
       0                               0
Bank Sta=9935.423,10074.41
Exp/Cntr=0.3,0.1

Type RM Length L Ch R = 1 ,17084.86,108.168200,108.168200,108.168200
XS GIS Cut Line= 6
924617.671884241 807391.96120235924629.824662019807324.252869017
924688.852439797 807266.96120235924713.157995352807240.919535683
924735.727439797807168.002869017924753.088550908807098.558424572
#Sta/Elev= 30
9802.527152.90449819.759152.02529829.919 151.4199850.238149.48139871.317146.7105
9878.529145.88499892.465143.8653 9898.96143.02629906.401142.22269920.336140.5615
9934.272139.16269948.208138.11699969.938136.96929989.198136.40119995.428136.5415
10005.86135.785710016.33136.5492 10026.8136.925610037.27137.435110047.74 138.255
 10058.2 139.52810063.07139.875510068.62 140.43110078.93141.727910099.55144.5901
10103.76144.932110109.85145.706910120.16147.653110130.47149.313410137.11150.2057
#Mann= 3 , 0 , 0
9802.527    0.04       09802.527    0.04       010137.11    0.04       0
#XS Ineff= 2 , 0
       0                               0
Bank Sta=9802.527,10137.11
Exp/Cntr=0.3,0.1

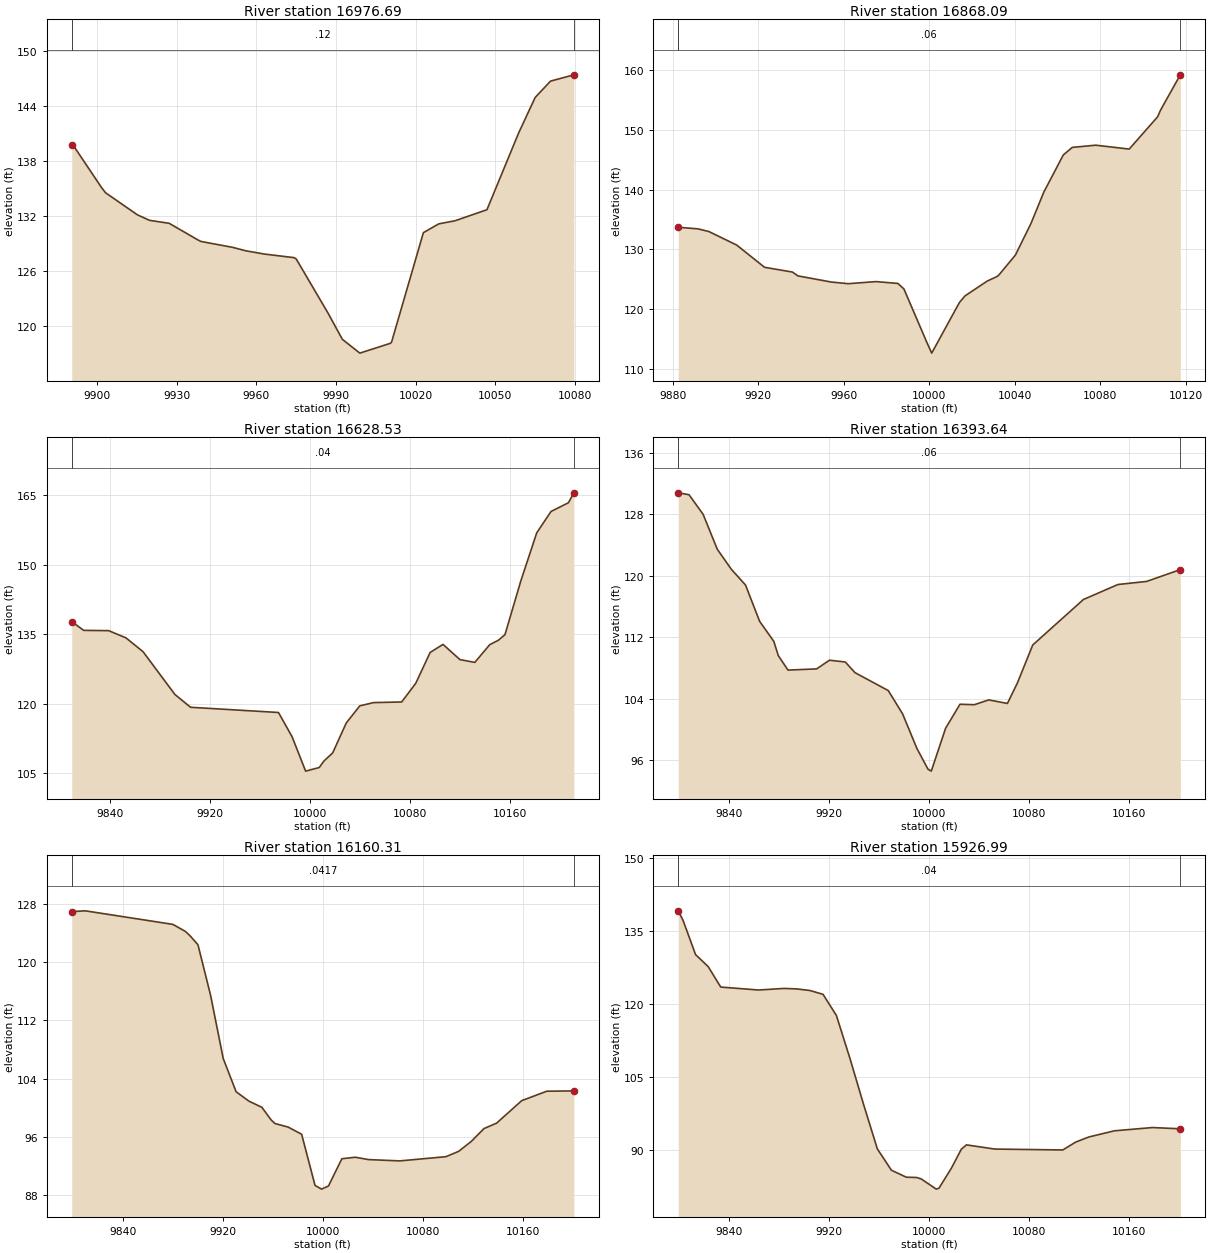
Type RM Length L Ch R = 1 ,16976.69,108.604300,108.604300,108.604300
XS GIS Cut Line= 2
924871.144106463807275.641757905924766.977439797807117.655646794
#Sta/Elev= 28
9890.393139.78119891.161139.62619901.554135.13869903.139134.54369915.117132.1412
9919.721131.53659927.095131.21629937.888129.41169939.073129.23539951.051 128.591
9956.054128.21239963.029127.85849974.221127.46719975.007127.31919986.985121.4199
9992.388118.55769998.964117.054910010.55118.133310010.94118.266410022.92 130.194
10028.72131.1526 10034.9131.494410046.88132.698510046.89132.704710058.85141.0832
10065.05144.936510070.83146.720910079.63147.4091
#Mann= 3 , 0 , 0
9890.393    0.12       09890.393    0.12       010079.63    0.12       0
#XS Ineff= 2 , 0
       0                               0
Bank Sta=9890.393,10079.63
Exp/Cntr=0.3,0.1

Type RM Length L Ch R = 1 ,16868.09,239.557200,239.557200,239.557200
XS GIS Cut Line= 5
924960.920592075807195.960228139 924886.22889049807106.677912668
924884.993014005807105.105459389924865.620122477807081.617701239
924808.877621106807017.048228929
#Sta/Elev= 29
9882.595133.70649891.822133.44349896.885133.00069909.922130.7429 9922.96127.0305
9935.998126.23489938.576125.59479954.161124.57199962.074124.29379975.112124.6427
 9985.33 124.333 9988.15123.4118    9999 114.39610001.14112.7075 10014.1121.1495
10016.71122.253510027.06124.720910031.45125.453510032.39125.673410040.26129.0557
10047.53134.306410053.57139.571210062.68145.772110066.88147.033710077.83147.4029
10093.51146.752910106.82  152.1510108.13153.229110117.41159.1431
#Mann= 3 , 0 , 0
9882.595    0.06       09882.595    0.06       010117.41    0.06       0
#XS Ineff= 2 , 0
       0                               0
Bank Sta=9882.595,10117.41
Exp/Cntr=0.3,0.1

Type RM Length L Ch R = 1 ,16628.53,234.888500,234.888500,234.888500
XS GIS Cut Line= 6
925205.066782002807051.973324587925162.824990598 807009.29906591
925120.693658298806977.150684391925077.184467607806952.527319901
924970.034735326806903.851037874924871.573786411806833.752585144
#Sta/Elev= 30
9809.423137.69699818.921135.81099838.979135.74829852.788134.19319866.518131.1935
9891.926 121.9829904.505119.20049974.868118.07419985.736112.84789996.604105.4123
10007.47106.189610011.32107.614110018.27109.353910029.08115.7948 10039.9119.5004
10050.95120.211210073.44120.345510084.69124.359210096.27131.047210106.57132.7807
10120.09129.4965   10132128.894110143.91132.713510150.92133.686510156.14134.8877
10168.83146.491410181.53156.854210192.99161.484610206.91163.367610211.26165.5135
#Mann= 3 , 0 , 0
9809.423    0.04       09809.423    0.04       010211.26    0.04       0
#XS Ineff= 2 , 0
       0                               0
Bank Sta=9809.423,10211.26
Exp/Cntr=0.3,0.1

Type RM Length L Ch R = 1 ,16393.64,233.329000,233.329000,233.329000
XS GIS Cut Line= 5
925272.484328603806932.620243509925232.994855868806858.069590994
925176.401009816806757.244254915925175.356702096806755.538552307
925076.760874979806581.533922604
#Sta/Elev= 30
9799.014 130.7799807.637130.53669818.953127.9811 9830.27123.43929841.586120.8229
9852.902118.77979864.218114.04879875.535111.46079879.094109.61529886.897107.7146
9909.833 107.8749920.141109.00299932.768108.76899940.572107.38079967.171105.0534
9978.638102.02749990.10697.52379    9999 94.824510001.6294.5723610013.11100.1605
10024.61103.2741 10036.1103.214210047.59103.836910062.58103.378210070.58106.0471
10082.86110.984510123.43116.900510151.04118.850810174.03119.2506   10201120.7923
#Mann= 3 , 0 , 0
9799.014    0.06       09799.014    0.06       0   10201    0.06       0
#XS Ineff= 2 , 0
       0                               0
Bank Sta=9799.014,10201
Exp/Cntr=0.3,0.1

Type RM Length L Ch R = 1 ,16160.31,233.328900,233.328900,233.328900
XS GIS Cut Line= 6
925367.458797121806925.818465039925364.841147388 806865.81828224
925370.697832399806805.233464806925417.923773061806661.063878721
925429.571201018806597.651138819925435.472905307806533.452093407
#Sta/Elev= 30
 9799.09126.89779809.919127.00679880.004 125.1519890.023124.18719893.931123.5579
9900.093 122.3619910.197 115.4319920.306  106.779930.618102.21689940.929100.9234
 9951.24100.08049958.48898.388029961.66997.865739972.304 97.37029983.07996.38685
9993.78489.37944    999988.8701310004.5389.2988610015.2793.0334110026.0193.24102
 10036.692.9174210061.6892.7388910098.4993.3140310108.6694.0398310118.8295.40165
10128.9997.1657710139.1297.9130410159.21100.996110179.29102.288810200.93102.3286
#Mann= 3 , 0 , 0
 9799.09  0.0417       0 9799.09  0.0417       010200.93  0.0417       0
#XS Ineff= 2 , 0
       0                               0
Bank Sta=9799.09,10200.93
Exp/Cntr=0.3,0.1

Type RM Length L Ch R = 1 ,15926.99,233.328900,233.328900,233.328900
XS GIS Cut Line= 6
925551.798779587806988.785844178925558.556972982806928.983211409
925573.560895523806870.119991319925591.816021517806828.521442799
925650.083983365806730.368365134925678.248250768806613.023231957
#Sta/Elev= 30
9799.134139.13739802.944 137.2059813.008130.14779823.072127.69989833.135123.4859
9863.395122.8757 9883.87123.2019 9894.11123.0986 9904.56122.7736 9915.01121.9895
9925.701117.65179936.621108.76519947.542    99.39958.462 90.25529969.72985.87009
9981.63184.443139989.84684.380929993.534 84.091510005.6181.9916110007.8182.19109
10017.6986.2847910025.6690.1870810029.7691.0785110052.4390.2169610106.8590.03486
10117.2291.6566910127.5892.6913610148.1693.96627 10178.694.6359310200.8994.38075
#Mann= 3 , 0 , 0
9799.134    0.04       09799.134    0.04       010200.89    0.04       0
#XS Ineff= 2 , 0
       0                               0
Bank Sta=9799.134,10200.89
Exp/Cntr=0.3,0.1

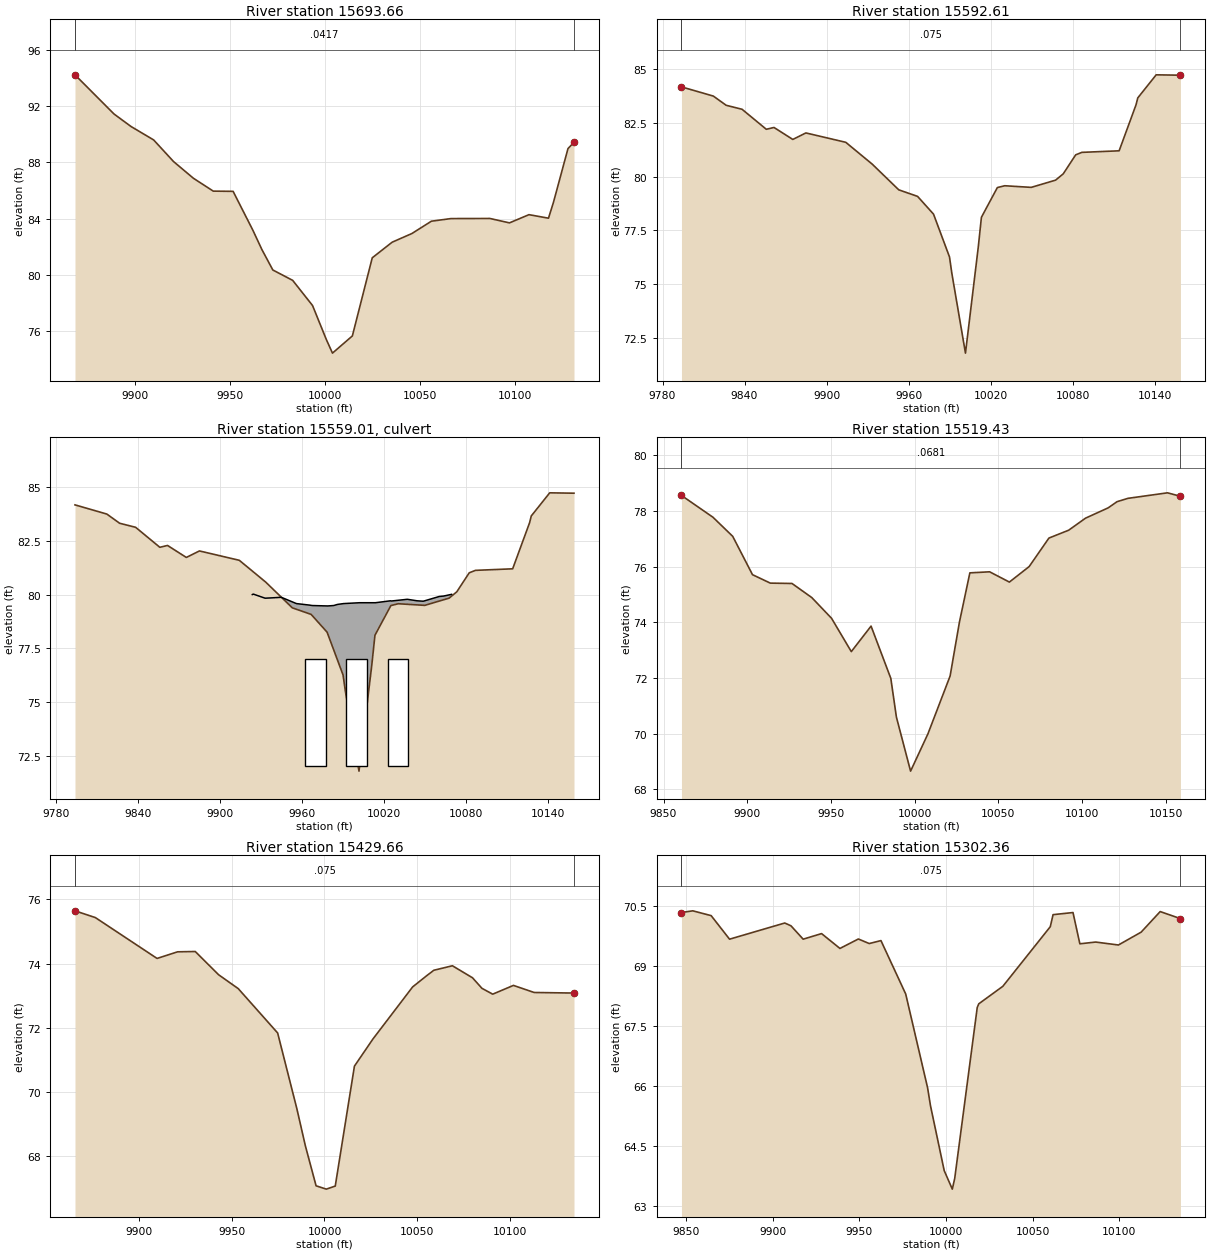
Type RM Length L Ch R = 1 ,15693.66,101.049400,101.049400,101.049400
XS GIS Cut Line= 5
925873.571752676806934.631609224925835.701651216806809.923479016
925835.025692588806808.041171938925822.965990917806769.359107296
925802.539156249806681.920781485
#Sta/Elev= 28
9868.66994.216719889.18591.436069898.16990.544359910.08789.588889920.538 88.0539
9930.98986.86824 9941.4485.952449951.89185.936529962.342 83.16159966.99981.81267
9972.79380.349649983.24479.611529993.69577.82544   1000175.3942110004.1974.44099
10014.66 75.663810025.1381.2150610035.6182.3243910045.9982.9394210056.2683.81548
10066.5384.0012910087.0784.0092710097.3483.6963110107.6184.2795210117.8884.02951
10120.4985.1509510128.1588.9766810131.31 89.4244
#Mann= 3 , 0 , 0
9868.669  0.0417       09868.669  0.0417       010131.31  0.0417       0
#XS Ineff= 2 , 0
       0                               0
Bank Sta=9868.669,10131.31
Exp/Cntr=0.3,0.1

Type RM Length L Ch R = 1 ,15592.61,73.175300,73.175300,73.175300
XS GIS Cut Line= 3
926037.028271127806952.998445272925898.343876095806722.730015785
925832.926708627806652.079474919
#Sta/Elev= 30
9793.83784.173089817.15183.745159826.52183.317199838.19583.129869855.91682.19931
9861.54282.284399875.29981.727229884.88982.029629914.06481.593739933.44780.57588
9952.82979.382349966.60579.077259978.27878.250189989.95276.258699991.59475.52606
10001.6371.7841910010.9876.70751 10013.378.1050510024.9779.4880110030.3679.57224
10049.7479.4968610067.57 79.833310073.1880.1277910082.2881.0115210086.8181.12574
10114.06 81.198210126.4483.3423510127.6983.6584710141.1684.7336310158.9384.71628
#Mann= 3 , 0 , 0
9793.837   0.075       09793.837   0.075       010158.93   0.075       0
#XS Ineff= 2 , 0
       0                               0
Bank Sta=9793.837,10158.93
Exp/Cntr=0.3,0.1

Type RM Length L Ch R = 2 ,15559.01,,,
Bridge Culvert--1,0,-1,-1, 0
Deck Dist Width WeirC Skew NumUp NumDn MinLoCord MaxHiCord MaxSubmerge Is_Ogee
19.088,35,2.6,0,23,23, , , 0.95, 0, 0,0,,
 9923.57 9924.36 9932.95 9944.40 9944.89 9955.85 9965.41 9967.30 9978.75 9983.15
 9985.79 9990.3410002.0010005.2310013.6610024.6610025.3210036.9810044.1010048.64
10060.3110063.5410069.38
   80.00   80.02   79.83   79.87   79.87   79.58   79.51   79.49   79.47   79.49
   79.54   79.58   79.62   79.62   79.62   79.71   79.70   79.78   79.71   79.69
   79.91   79.93   80.01
                                                                                
                                                                                
                        
 9923.57 9924.36 9932.95 9944.40 9944.89 9955.85 9965.41 9967.30 9978.75 9983.15
 9985.79 9990.3410002.0010005.2310013.6610024.6610025.3210036.9810044.1010048.64
10060.3110063.5410069.38
   80.00   80.02   79.83   79.87   79.87   79.58   79.51   79.49   79.47   79.49
   79.54   79.58   79.62   79.62   79.62   79.71   79.70   79.78   79.71   79.69
   79.91   79.93   80.01
                                                                                
                                                                                
                        
BR Coef=-1 , 0 , 0 ,, 0 ,,,0.8,-1,,0,
WSPro=,,,, 1 ,,,, 0 ,,,, 0 ,,,,-1 ,-1 ,-1 , 0 , 0 , 0 , 0 , 0
Multiple Barrel Culv=2,5,15.09,35,0.013,0.5,1,10,1,72,68,3,Culvert #1, 0, 19.088
 9969.82 9969.8210000.0010000.0010030.1810030.18
Culvert Bottom n=0.013
BC Design=,, 0 ,, 0 ,,,,,,

Type RM Length L Ch R = 1 ,15519.43,89.775300,89.775300,89.775300
XS GIS Cut Line= 2
926063.195138114806850.947664022925904.885592841806598.437397596
#Sta/Elev= 28
9860.70578.552069879.52877.769339891.33177.082929903.13475.707839913.78575.40475
9926.73975.391749938.54274.886089950.34574.142889962.14872.94602 9973.9573.86198
9985.75371.984279989.08970.594199997.55668.6561710007.9269.9952410021.1672.07045
10026.7474.0080710032.96 75.772910044.7775.8105310056.5775.4421710068.3775.99861
10080.1877.0221110091.9877.3041610102.0477.7362810115.5878.1067910120.8778.32839
10127.3978.4479210150.9978.6458410158.7478.52206
#Mann= 3 , 0 , 0
9860.705  0.0681       09860.705  0.0681       010158.74  0.0681       0
#XS Ineff= 2 , 0
       0                               0
Bank Sta=9860.705,10158.74
Exp/Cntr=0.3,0.1

Type RM Length L Ch R = 1 ,15429.66,127.299000,127.299000,127.299000
XS GIS Cut Line= 6
926123.188783258806824.897499116926090.469407903806757.031753772
 926079.22609876 806725.85129641926056.573295072806648.016573496
926043.901476179806617.628376962926022.915685006  806575.7815132
#Sta/Elev= 25
9865.352 75.6455 9876.3475.434829909.645 74.15969920.74674.366029930.26174.37585
9942.85373.651039953.48473.216419974.72371.833539985.09869.469649989.68668.31215
9995.47467.06238   1000166.9593710005.8267.0545910016.1770.7977310026.1671.64556
10047.5873.2703110054.9373.6098710059.0273.7903810069.0473.9309110079.8773.55674
   1008573.22632 10090.873.0443510101.9873.3179110113.1773.0968110134.6773.07906
#Mann= 3 , 0 , 0
9865.352   0.075       09865.352   0.075       010134.67   0.075       0
#XS Ineff= 2 , 0
       0                               0
Bank Sta=9865.352,10134.67
Exp/Cntr=0.3,0.1

Type RM Length L Ch R = 1 ,15302.36,360.068500,360.068500,360.068500
XS GIS Cut Line= 6
926246.363207024806771.138719711926209.729593242806669.087938461
926179.450037249806638.138072831926177.917516092806636.853012948
926142.656957857806602.812047842 926087.43134332806537.667803618
#Sta/Elev= 30
9847.27570.347589853.79770.390699864.42270.270389875.04769.681119906.92170.08567
9910.50570.016429917.54669.681079928.17169.820999938.79569.44922 9949.4269.68581
9955.70269.571779962.46569.645669976.76468.30916  9989.465.962029991.06465.51476
    999963.8884510003.6763.4258910005.0663.6931910018.07 67.972510018.9568.06321
10032.8568.5019210060.25 69.993710061.8570.2946810073.3670.3476310077.3269.56541
10086.4769.6091910099.5869.5354310112.6969.8566410123.7170.3718310135.41 70.1957
#Mann= 3 , 0 , 0
9847.275   0.075       09847.275   0.075       010135.41   0.075       0
#XS Ineff= 2 , 0
       09899.078                       0
Bank Sta=9847.275,10135.41
Exp/Cntr=0.3,0.1

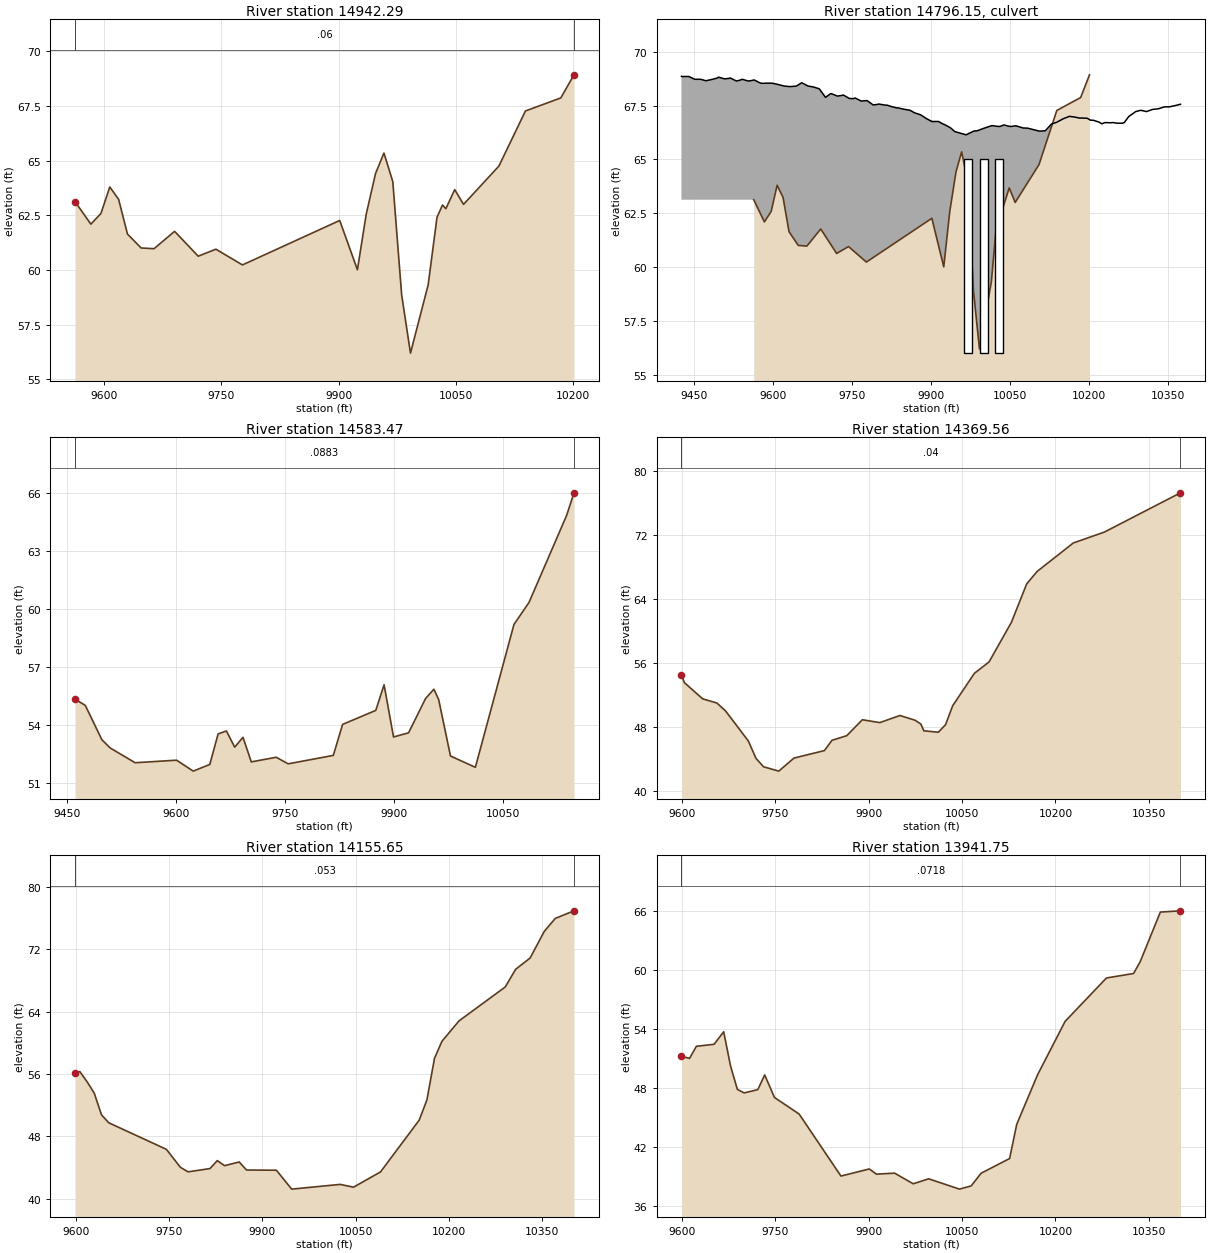
Type RM Length L Ch R = 1 ,14942.29,358.818400,358.818400,358.818400
XS GIS Cut Line= 2
926574.486120352806724.345099919926276.498924172806160.108988808
#Sta/Elev= 30
9562.86963.127229583.18262.095159596.05562.582469607.36463.794959618.67363.22931
9629.98261.640649647.42261.005479663.90960.971059690.24961.765889720.453 60.6283
9743.07160.948879776.99860.228679901.39662.263169924.01460.007869935.32362.55746
9947.20964.41368 9957.9465.348359969.24964.041199980.55858.865459991.86756.19331
10014.4959.3183810025.79 62.409510032.8662.97206 10037.162.7999810048.41 63.6752
10059.7262.9992610104.9664.7534310138.8867.2733610184.1267.8710910200.9668.92724
#Mann= 3 , 0 , 0
9562.869    0.06       09562.869    0.06       010200.96    0.06       0
#XS Ineff= 2 , 0
       09878.642                       0
Bank Sta=9562.869,10200.96
Exp/Cntr=0.3,0.1

Type RM Length L Ch R = 2 ,14796.15,,,
Bridge Culvert--1,0,-1,-1, 0
Deck Dist Width WeirC Skew NumUp NumDn MinLoCord MaxHiCord MaxSubmerge Is_Ogee
50.909,257,2.6,0,130,130, , , 0.95, 0, 0,0,,
 9425.57 9428.15 9429.43 9439.45 9450.75 9450.92 9462.05 9472.40 9473.35 9484.65
 9493.89 9495.94 9507.24 9515.37 9518.54 9529.84 9536.86 9541.14 9552.43 9558.35
 9563.73 9575.03 9579.83 9586.33 9597.63 9601.32 9608.93 9620.22 9622.80 9631.52
 9642.82 9644.29 9654.12 9665.42 9665.77 9676.72 9687.26 9688.01 9699.31 9708.75
 9710.61 9721.91 9730.23 9733.21 9744.51 9751.72 9755.80 9767.10 9773.20 9778.40
 9789.70 9794.69 9801.00 9812.30 9816.18 9823.59 9834.89 9837.66 9846.19 9857.49
 9859.15 9868.79 9880.09 9880.63 9891.38 9902.12 9902.68 9913.98 9923.61 9925.28
 9936.58 9945.09 9947.88 9959.17 9966.58 9970.47 9981.77 9988.06 9993.0710004.37
10009.5510015.6710026.9610031.0410038.2610049.5610052.5210060.8610072.1610074.01
10083.4510094.7510095.4910106.0510116.9810117.3510128.6510138.4610139.9510151.24
10159.9510162.5410173.8410181.4410185.1410196.4410202.9210207.7410219.0310224.41
10230.3310241.6310245.8910252.9310264.2310267.3810275.5310286.8210288.8710298.12
10309.4210310.3510320.7210331.8410332.0210343.3210353.3210354.6110365.9110373.81
   68.86   68.84   68.85   68.85   68.72   68.72   68.72   68.65   68.66   68.72
   68.78   68.82   68.74   68.76   68.78   68.64   68.68   68.72   68.64   68.66
   68.69   68.55   68.53   68.54   68.54   68.52   68.48   68.41   68.40   68.38
   68.40   68.41   68.56   68.42   68.41   68.36   68.28   68.26   67.88   68.05
   68.05   67.94   67.97   67.99   67.83   67.82   67.85   67.71   67.72   67.73
   67.53   67.54   67.57   67.52   67.52   67.46   67.39   67.39   67.34   67.29
   67.29   67.16   67.07   67.06   66.89   66.75   66.76   66.76   66.63   66.62
   66.47   66.29   66.27   66.19   66.14   66.19   66.32   66.33   66.38   66.48
   66.52   66.57   66.53   66.53   66.60   66.53   66.53   66.56   66.48   66.46
   66.45   66.38   66.38   66.31   66.33   66.34   66.64   66.72   66.74   66.89
   66.97   67.00   66.96   66.92   66.92   66.91   66.82   66.82   66.73   66.65
   66.71   66.70   66.71   66.68   66.68   66.72   66.99   67.19   67.22   67.28
   67.22   67.23   67.32   67.35   67.35   67.44   67.44   67.45   67.51   67.56
                                                                                
                                                                                
                                                                                
                                                                                
                                                                                
                                                                                
                                                                                
                                                                                
                                                                                
                                                                                
                                                                                
                                                                                
                                                                                
 9425.57 9428.15 9429.43 9439.45 9450.75 9450.92 9462.05 9472.40 9473.35 9484.65
 9493.89 9495.94 9507.24 9515.37 9518.54 9529.84 9536.86 9541.14 9552.43 9558.35
 9563.73 9575.03 9579.83 9586.33 9597.63 9601.32 9608.93 9620.22 9622.80 9631.52
 9642.82 9644.29 9654.12 9665.42 9665.77 9676.72 9687.26 9688.01 9699.31 9708.75
 9710.61 9721.91 9730.23 9733.21 9744.51 9751.72 9755.80 9767.10 9773.20 9778.40
 9789.70 9794.69 9801.00 9812.30 9816.18 9823.59 9834.89 9837.66 9846.19 9857.49
 9859.15 9868.79 9880.09 9880.63 9891.38 9902.12 9902.68 9913.98 9923.61 9925.28
 9936.58 9945.09 9947.88 9959.17 9966.58 9970.47 9981.77 9988.06 9993.0710004.37
10009.5510015.6710026.9610031.0410038.2610049.5610052.5210060.8610072.1610074.01
10083.4510094.7510095.4910106.0510116.9810117.3510128.6510138.4610139.9510151.24
10159.9510162.5410173.8410181.4410185.1410196.4410202.9210207.7410219.0310224.41
10230.3310241.6310245.8910252.9310264.2310267.3810275.5310286.8210288.8710298.12
10309.4210310.3510320.7210331.8410332.0210343.3210353.3210354.6110365.9110373.81
   68.86   68.84   68.85   68.85   68.72   68.72   68.72   68.65   68.66   68.72
   68.78   68.82   68.74   68.76   68.78   68.64   68.68   68.72   68.64   68.66
   68.69   68.55   68.53   68.54   68.54   68.52   68.48   68.41   68.40   68.38
   68.40   68.41   68.56   68.42   68.41   68.36   68.28   68.26   67.88   68.05
   68.05   67.94   67.97   67.99   67.83   67.82   67.85   67.71   67.72   67.73
   67.53   67.54   67.57   67.52   67.52   67.46   67.39   67.39   67.34   67.29
   67.29   67.16   67.07   67.06   66.89   66.75   66.76   66.76   66.63   66.62
   66.47   66.29   66.27   66.19   66.14   66.19   66.32   66.33   66.38   66.48
   66.52   66.57   66.53   66.53   66.60   66.53   66.53   66.56   66.48   66.46
   66.45   66.38   66.38   66.31   66.33   66.34   66.64   66.72   66.74   66.89
   66.97   67.00   66.96   66.92   66.92   66.91   66.82   66.82   66.73   66.65
   66.71   66.70   66.71   66.68   66.68   66.72   66.99   67.19   67.22   67.28
   67.22   67.23   67.32   67.35   67.35   67.44   67.44   67.45   67.51   67.56
                                                                                
                                                                                
                                                                                
                                                                                
                                                                                
                                                                                
                                                                                
                                                                                
                                                                                
                                                                                
                                                                                
                                                                                
                                                                                
BR Coef=-1 , 0 , 0 ,, 0 ,,,0.8,-1,,0,
WSPro=,,,, 1 ,,,, 0 ,,,, 0 ,,,,-1 ,-1 ,-1 , 0 , 0 , 0 , 0 , 0
Multiple Barrel Culv=2,9,14.76,257,0.013,0.7,1,8,3,56,52,3,Culvert #1, 0, 50.909
 9970.48 9970.4810000.0010000.0010029.5210029.52
Culvert Bottom n=0.013
BC Design=,, 0 ,, 0 ,,,,,,

Type RM Length L Ch R = 1 ,14583.47,213.908100,213.908100,213.908100
XS GIS Cut Line= 2
926856.604175908806537.441888114 926525.11546063805936.177782211
#Sta/Elev= 30
9460.509 55.34269474.71655.013959497.55453.240439508.97452.818669543.23152.05743
9600.326 52.18819623.16451.623919646.00251.968789657.42253.543079668.841 53.6975
 9680.2652.861529691.67953.368489703.09852.100079737.35552.339399753.80352.00045
 9815.9452.435059828.70854.034729874.38454.759249885.80356.080119898.78953.38601
9919.50153.600749942.89955.371999954.31855.852799960.92655.314659977.15652.40526
10011.4151.8201710064.4959.19232 10085.260.3291210137.0264.82626 10147.165.98646
#Mann= 3 , 0 , 0
9460.509  0.0883       09460.509  0.0883       0 10147.1  0.0883       0
#XS Ineff= 2 , 0
       09867.795                       0
Bank Sta=9460.509,10147.1
Exp/Cntr=0.3,0.1

Type RM Length L Ch R = 1 ,14369.56,213.908100,213.908100,213.908100
XS GIS Cut Line= 6
927102.964818721 806177.72557541926787.115080545805957.862186855
926765.973037002805941.369649146926706.195417201805906.386079632
926656.636595733805873.755363724926447.101380165805717.027654066
#Sta/Elev= 30
9599.01754.501099603.75953.557369633.19351.531959655.94951.012759669.85550.02668
9706.51746.264869718.73844.095129730.95943.03403  9755.442.490889779.84244.12148
9828.725 45.05939840.94646.34656 9864.7146.928259889.70948.920239917.775 48.5597
9950.15549.450399974.333 48.86049983.86648.377139988.57547.5354510011.82 47.3555
10023.4148.2983110034.9950.6834310069.7554.7227310093.3656.1521810129.2861.10857
10153.82 65.9135 10170.667.4729810228.7571.03586 10278.7 72.399710400.96 77.3104
#Mann= 3 , 0 , 0
9599.017    0.04       09599.017    0.04       010400.96    0.04       0
#XS Ineff= 2 , 0
       09937.647                       0
Bank Sta=9599.017,10400.96
Exp/Cntr=0.3,0.1

Type RM Length L Ch R = 1 ,14155.65,213.908000,213.908000,213.908000
XS GIS Cut Line= 6
927181.695433283805970.659440883926927.211306381805818.424554953
926879.125977005805784.522679317926710.439437378805650.074610049
926623.891369833805593.605116766926513.252837213 805530.57353803
#Sta/Elev= 30
9599.03556.151289606.79556.298079618.38755.010059630.00153.530449641.56950.76004
9653.16149.739469745.89146.326249768.42744.021769780.70243.439959815.94943.85722
9827.69844.878749839.44844.231699862.94644.703479874.69543.673429922.772 43.6424
9947.24341.2202810025.2641.82774 10046.641.4696110089.97 43.423110152.1550.06639
10164.5952.6641110176.7558.00432 10188.760.1830710216.15  62.80510290.4267.15609
10307.2269.42697 10330.570.8802210353.3274.3111510370.9975.9606110400.9576.92844
#Mann= 3 , 0 , 0
9599.035   0.053       09599.035   0.053       010400.95   0.053       0
#XS Ineff= 2 , 0
       09855.591                       0
Bank Sta=9599.035,10400.95
Exp/Cntr=0.3,0.1

Type RM Length L Ch R = 1 ,13941.75,213.908100,213.908100,213.908100
XS GIS Cut Line= 6
927336.837544586805776.617609942927080.875127836 805655.31717607
 927014.84771997805615.998675447926937.464194439805559.740271236
926862.330536587 805518.00747721926624.909348178805412.185900252
#Sta/Elev= 30
9599.06251.223639612.05351.006469623.02852.233869651.53252.439279666.92753.70818
9677.90250.245659688.87747.854479699.85147.498869721.801 47.83449732.77549.32278
9748.61947.03078 9788.1445.354529855.351   39.059900.85239.769789912.49139.24395
 9941.6339.346469971.46538.264169996.32838.7703710045.8737.7227110064.6938.05222
10080.6339.3388210126.3940.8320310137.8244.3008610171.2149.32297 10215.654.76739
10282.0359.1768110325.5959.6301610336.4160.8548810368.6365.8711110400.9565.99876
#Mann= 3 , 0 , 0
9599.062  0.0718       09599.062  0.0718       010400.95  0.0718       0
#XS Ineff= 2 , 0
       0                               0
Bank Sta=9599.062,10400.95
Exp/Cntr=0.3,0.1

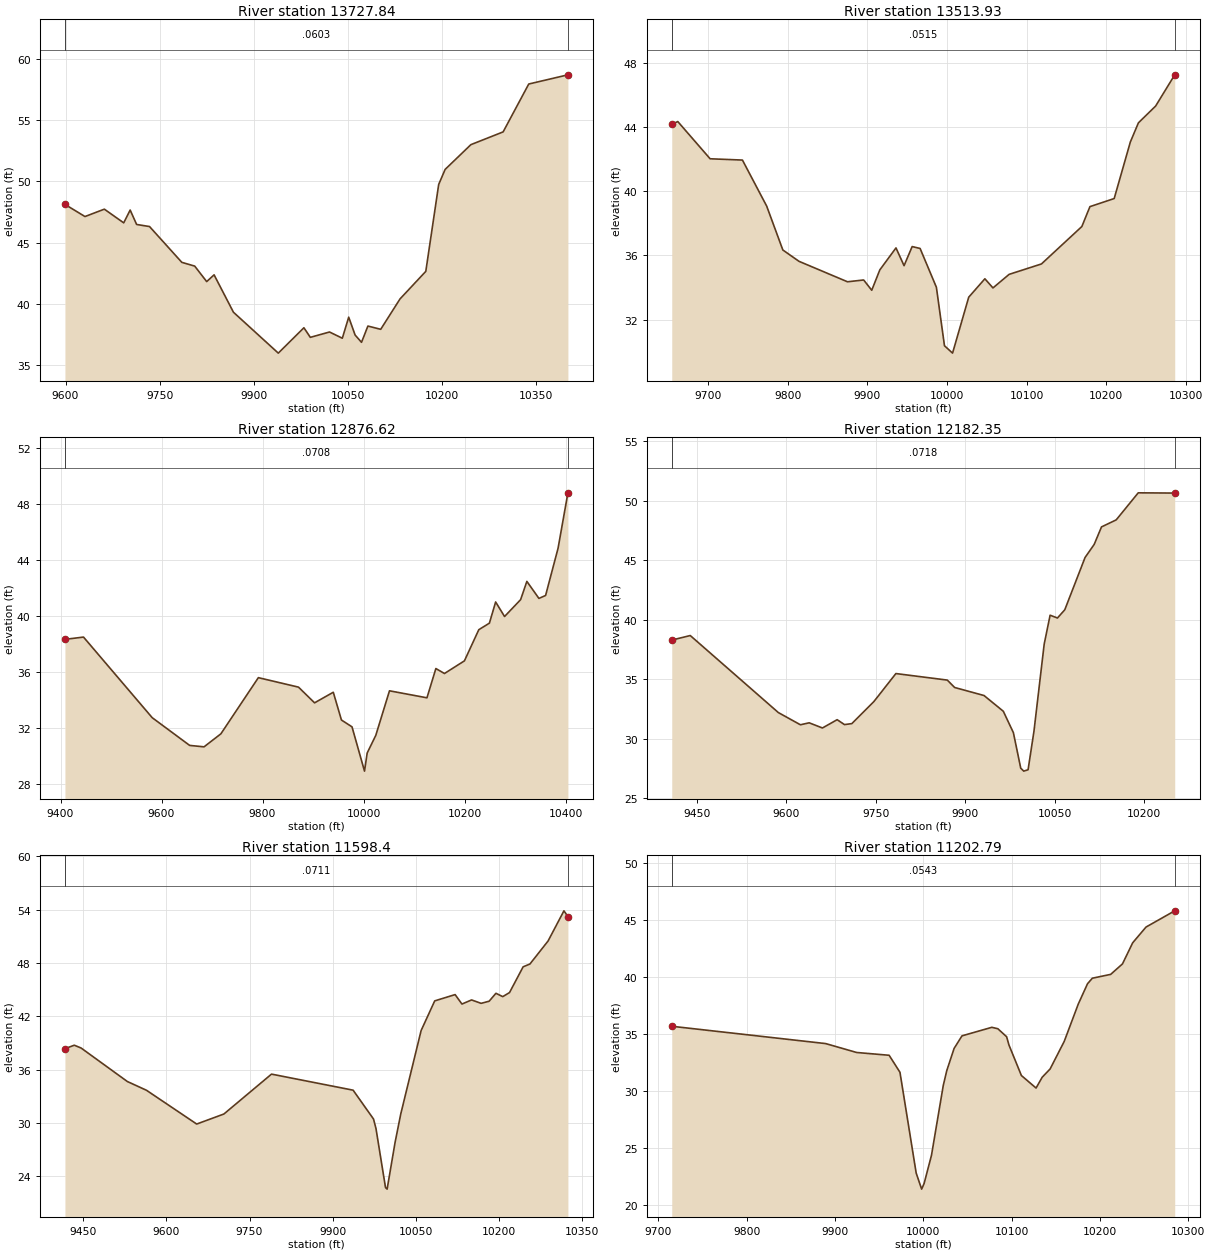
Type RM Length L Ch R = 1 ,13727.84,213.908100,213.908100,213.908100
XS GIS Cut Line= 6
927426.048896427805478.518701299927164.420304466805414.749465826
927036.445918473805388.189615408926931.455380627805366.971749665
926741.867868859 805322.26871525926643.858700494   805301.989743
#Sta/Elev= 30
9599.011 48.12529630.96847.130619661.84747.734299692.72546.614399703.01847.66297
 9713.31 46.48179733.89646.31215 9785.3643.382969805.94543.074329825.01241.80669
9836.82442.359659867.70239.298529939.19835.952389980.051 38.02959990.26437.24387
10020.8837.6814410041.2837.1725110051.4838.8944210061.6937.4321610071.8936.83648
10082.0938.16842 10102.537.9007910133.2940.3882510174.3942.6442910194.9449.75403
10205.2150.9880310246.3153.0152810297.6854.0576910338.5557.9767910400.9858.72923
#Mann= 3 , 0 , 0
9599.011  0.0603       09599.011  0.0603       010400.98  0.0603       0
#XS Ineff= 2 , 0
       0                               0
Bank Sta=9599.011,10400.98
Exp/Cntr=0.3,0.1

Type RM Length L Ch R = 1 ,13513.93,637.305900,637.305900,637.305900
XS GIS Cut Line= 2
927422.467891186805237.718580822926800.072057852805130.947747489
#Sta/Elev= 30
9654.33444.177739661.91144.351849702.49642.03021 9743.0841.950039773.51839.07902
 9793.8136.342269814.10335.635189874.97934.360139895.27134.472359905.41733.83204
9915.56335.102139935.856 36.47239946.002  35.3649956.14836.555649966.13436.43869
9986.58634.018749996.732 30.371810006.8829.9110610027.1733.3983310047.4634.54754
10057.6133.97659 10077.934.8225710118.4835.4718310169.2237.8065810179.3639.04613
 10209.839.5498610230.0943.0761510240.24 44.272810261.8645.3197610285.8247.26565
#Mann= 3 , 0 , 0
9654.334  0.0515       09654.334  0.0515       010285.82  0.0515       0
#XS Ineff= 2 , 0
       0                               0
Bank Sta=9654.334,10285.82
Exp/Cntr=0.3,0.1

Type RM Length L Ch R = 1 ,12876.62,694.275800,694.275800,694.275800
XS GIS Cut Line= 2
927227.028701997804195.249549291926641.217891186805000.739414155
#Sta/Elev= 30
9408.73738.320329445.52338.482949581.53832.720099655.72830.737249684.21530.63494
9717.55231.566169791.74235.581369871.23534.904219903.02733.781629940.12234.53812
9956.24532.554459977.217 32.063710001.95 28.898610007.2530.1969710024.2531.45245
10051.4134.64136 10125.634.1406910143.2636.2336810160.2735.8779310199.7936.78332
10228.2739.0109710249.2539.4789710261.6140.9932510279.2839.9534110311.0741.15926
10323.4442.4647110347.2941.2482610360.5341.4579210385.2644.8392710404.7248.79708
#Mann= 3 , 0 , 0
9408.737  0.0708       09408.737  0.0708       010404.72  0.0708       0
#XS Ineff= 2 , 0
       0                               0
Bank Sta=9408.737,10404.72
Exp/Cntr=0.3,0.1

Type RM Length L Ch R = 1 ,12182.35,583.949000,583.949000,583.949000
XS GIS Cut Line= 2
926659.447057852803789.801914155926167.259557852804474.697747489
#Sta/Elev= 30
 9407.6438.29158 9438.67  38.6759586.44232.200439623.38531.177239638.02731.34168
9660.32830.907859684.95731.603739697.27131.191349709.58631.275199746.52933.12388
9783.47235.480569869.672  34.9319881.98734.310199931.24433.635399963.60732.31203
9980.50130.514319992.81627.530529997.879 27.282210005.1327.3970310015.01 30.6364
10032.1537.9561510042.0740.3826110054.3940.14768 10066.740.8408510100.69 45.2336
10115.9646.3290110128.2747.80293 10152.9 48.392610189.85 50.665910251.0450.64569
#Mann= 3 , 0 , 0
 9407.64  0.0718       0 9407.64  0.0718       010251.04  0.0718       0
#XS Ineff= 2 , 0
       0                               0
Bank Sta=9407.64,10251.04
Exp/Cntr=0.3,0.1

Type RM Length L Ch R = 1 , 11598.4,395.612800,395.612800,395.612800
XS GIS Cut Line= 2
926180.280391186803451.260247489925654.238724519804190.843580822
#Sta/Elev= 30
9416.89138.358079433.752 38.75069446.02338.43733 9529.5234.668929564.02633.68376
9654.63929.887459703.72531.015319789.62635.499959936.88433.695039973.69930.45091
9978.09829.400449995.35122.746329998.24222.57007 10012.627.8209910022.78 30.9986
 10059.640.4005710084.1443.7348410120.9644.4418510133.2343.3797410150.6343.84085
10167.8843.4574910182.3143.6970510194.5944.5873910206.8644.2130510219.1344.67051
10243.6747.5642510255.9447.8800910288.6550.46494 10317.353.8600110324.4753.21433
#Mann= 3 , 0 , 0
9416.891  0.0711       09416.891  0.0711       010324.47  0.0711       0
#XS Ineff= 2 , 0
       0                               0
Bank Sta=9416.891,10324.47
Exp/Cntr=0.3,0.1

Type RM Length L Ch R = 1 ,11202.79,198.965900,198.965900,198.965900
XS GIS Cut Line= 6
925699.980870011803476.201095308925658.740260064 803517.63177402
925612.034860263803571.651511057925446.284537716803798.020806481
925401.133799292803854.058252189925343.484870051803919.356786189
#Sta/Elev= 30
 9715.2435.702729889.54934.181519924.58733.400389961.38533.155379973.65131.66192
9992.01822.809729998.18321.40032   1000121.8975410009.3224.3626510022.6930.50526
10026.6131.7963110034.9533.75657 10043.934.86231 10077.735.61119 10084.535.48421
10094.4234.7835510096.9834.0755810111.1431.3780910127.7630.2775510134.6731.22407
10143.6931.9556110159.6334.3704810175.5737.6543710186.0439.4385810191.5139.92322
10212.2740.2606210225.6141.1793810237.16 43.032610252.2744.4154410284.7845.84091
#Mann= 3 , 0 , 0
 9715.24  0.0543       0 9715.24  0.0543       010284.78  0.0543       0
#XS Ineff= 2 , 0
       0                               0
Bank Sta=9715.24,10284.78
Exp/Cntr=0.3,0.1