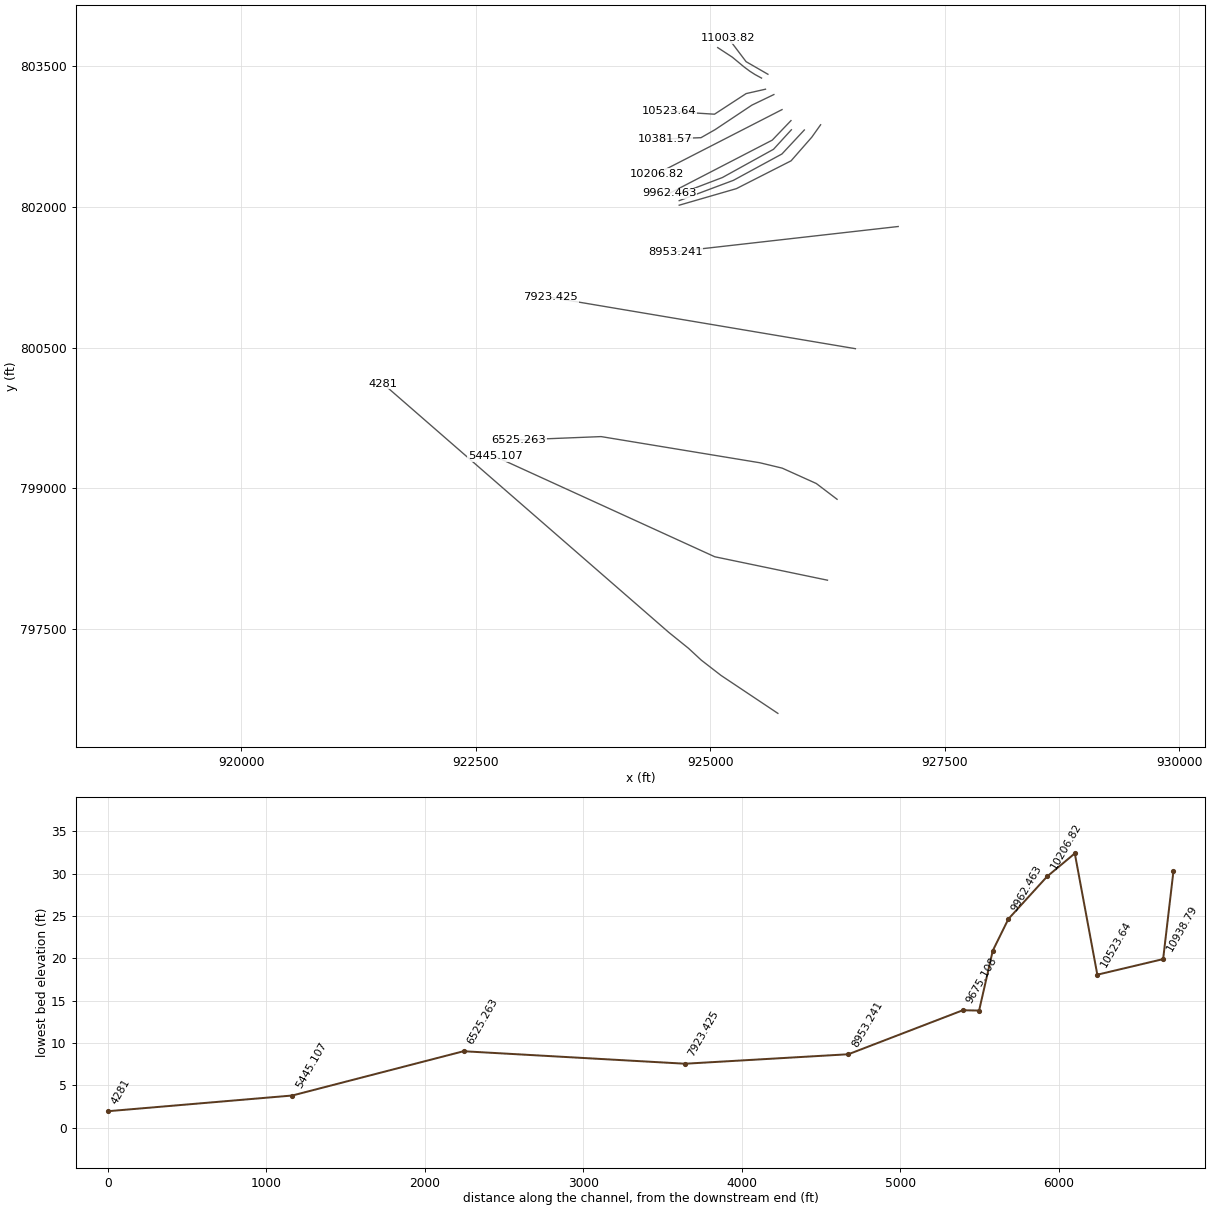
HEC-RAS study 13270_ras.prj: 13270

--- 13270_ras.g01 (geometry) --- (continued)

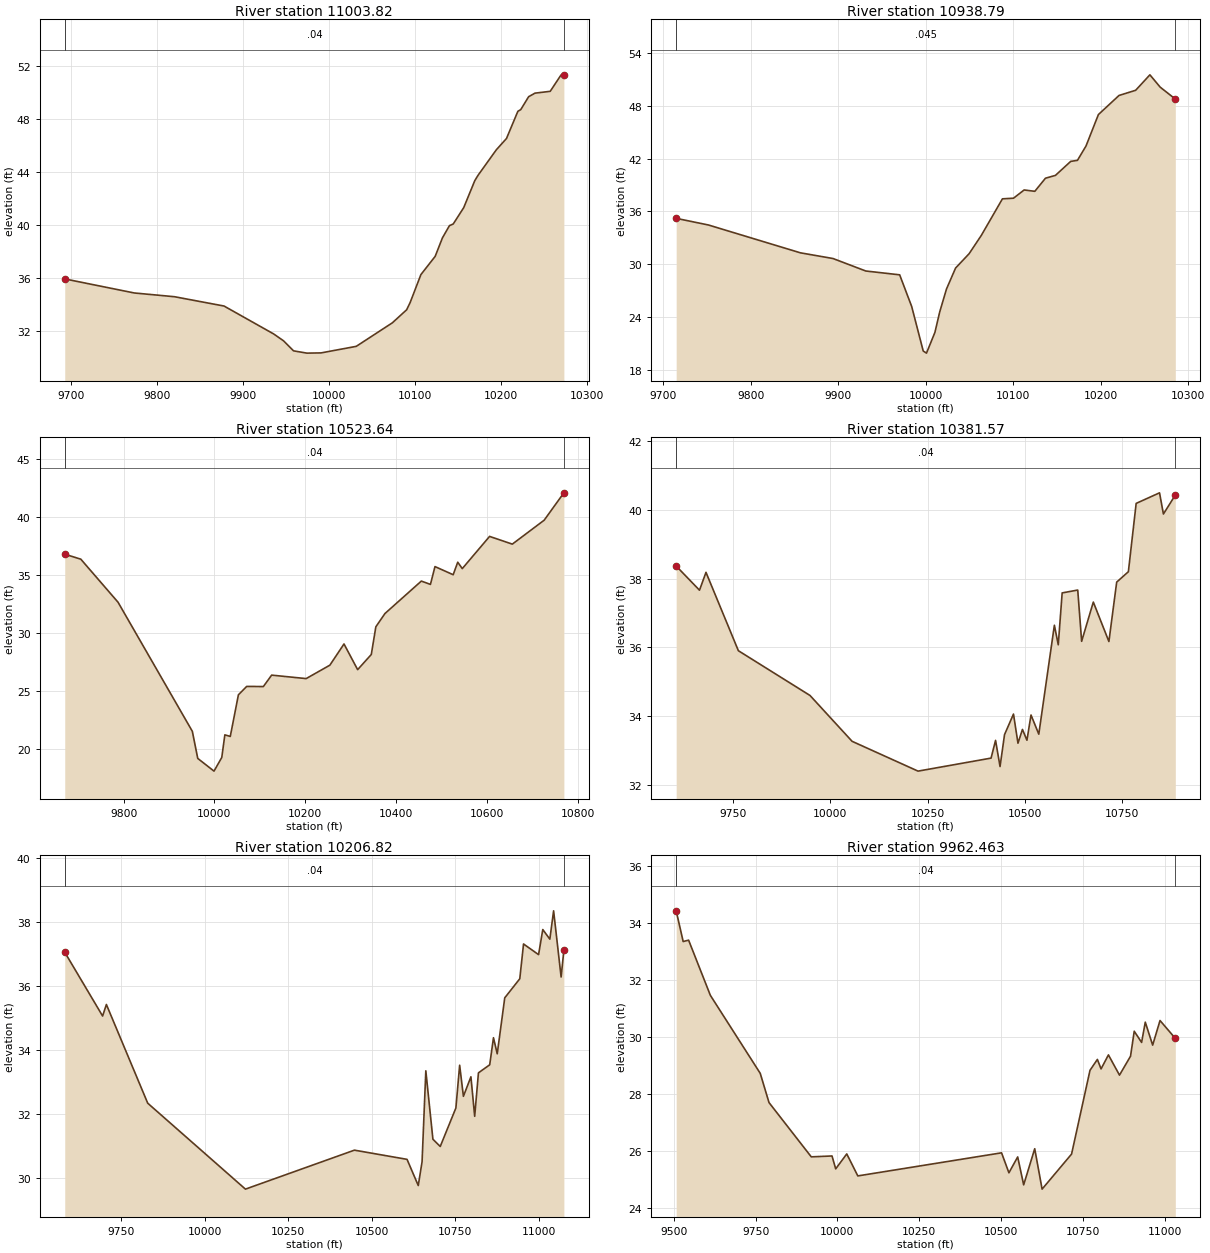
Type RM Length L Ch R = 1 ,11003.82,65.034100,65.034100,65.034100
XS GIS Cut Line= 3
925615.503377036803414.554868852925382.755981202803548.832212602
925194.767699952803797.692889686
#Sta/Elev= 30
9692.83835.894639773.77334.832559820.41334.551579878.13733.847269935.86131.73983
9947.40631.218739958.95130.464659974.40930.29173    999130.3084310031.9330.80384
10073.9532.5813810090.5433.56551 10094.634.1097210107.13 36.222610123.72 37.5979
10132.1938.9964910140.32 39.915810144.7340.0430210156.9141.2739110169.7943.31121
 10173.543.7103310194.8645.6441710206.6846.4974810219.92 48.551510223.2748.67807
10232.4549.6527810239.8649.9208810257.5250.0580310270.05 51.285710273.43 51.3039
#Mann= 3 , 0 , 0
9692.838    0.04       09692.838    0.04       010273.43    0.04       0
#XS Ineff= 2 , 0
       0                               0
Bank Sta=9692.838,10273.43
Exp/Cntr=0.3,0.1

Type RM Length L Ch R = 1 ,10938.79,415.147300,415.147300,415.147300
XS GIS Cut Line= 6
925547.467762602803373.722930533925477.688460531803411.734794137
925423.002898844803446.721861465 925363.14700746803491.287480991
925236.087256656803596.825551061925080.313361773803698.905218912
#Sta/Elev= 30
9714.74335.221279751.71634.463799856.75331.304879894.036  30.6579931.43929.24113
9970.20928.806149983.96825.201929997.13220.1515710000.8619.9136510010.4722.26249
10016.0324.6103410023.7627.2058610034.1229.5766310049.6131.2070310063.5133.28087
10087.67 37.4376 10100.337.5070710112.4938.4436310124.6838.2904110136.8739.77965
10148.2440.0979610165.7241.6890210173.4441.8093510183.2143.4391410197.3847.00942
10220.9249.1766810239.9549.7643410256.2351.52067   1026850.1201110285.2848.77022
#Mann= 3 , 0 , 0
9714.743   0.045       09714.743   0.045       010285.28   0.045       0
#XS Ineff= 2 , 0
       0                               0
Bank Sta=9714.743,10285.28
Exp/Cntr=0.3,0.1

Type RM Length L Ch R = 1 ,10523.64,142.066500,142.066500,142.066500
XS GIS Cut Line= 4
925589.460078686 803255.24245235925383.392462919803208.481996685
925046.116184552802988.600224048924561.682300908803019.131341239
#Sta/Elev= 30
 9670.4136.784139705.74736.35562 9787.7832.640829951.42221.50551 9963.3619.16633
9999.17218.0709210016.2719.2502610023.05 21.199810034.9821.0642110052.8924.65345
 10071.225.3789910107.8225.3649510126.1326.3518110202.1126.0528810254.3127.20958
10285.4629.0387510315.5226.8248610345.5728.1313910355.5930.5194310375.6331.66489
10455.7934.4636510475.8334.1785110485.8535.7148810525.9335.0130410535.9536.09201
10545.9735.5407410606.0938.3185910656.1937.6521910726.3339.7170210769.7342.07767
#Mann= 3 , 0 , 0
 9670.41    0.04       0 9670.41    0.04       010769.73    0.04       0
#XS Ineff= 2 , 0
       0                               0
Bank Sta=9670.41,10769.73
Exp/Cntr=0.3,0.1

Type RM Length L Ch R = 1 ,10381.57,174.756600,174.756600,174.756600
XS GIS Cut Line= 5
925678.978307852803198.222053044925444.603307852803085.374830822
925053.978307852802824.958164155 924902.06858563  802738.1526086
924524.464418963802725.131775266
#Sta/Elev= 30
9604.211 38.3632 9664.1237.660289680.79238.179869764.00935.898449947.99134.59589
10056.1633.2605410225.5732.3925910413.2632.7715310424.7733.2877910436.2932.52606
10447.8133.4544710470.8434.0542110482.3633.2057910493.8833.60673 10505.433.29239
10515.8534.0267910535.8633.4686310575.88 36.639710585.8936.0709910595.8937.58112
10635.92 37.664410645.9236.1715410675.9437.3145210715.9636.1658310735.9837.89577
10765.9938.1978610786.01 40.186910846.04 40.494910856.0539.87806 10886.6 40.4295
#Mann= 3 , 0 , 0
9604.211    0.04       09604.211    0.04       0 10886.6    0.04       0
#XS Ineff= 2 , 0
       0                               0
Bank Sta=9604.211,10886.6
Exp/Cntr=0.3,0.1

Type RM Length L Ch R = 1 ,10206.82,244.353300,244.353300,244.353300
XS GIS Cut Line= 2
925765.783863408803037.631775266924437.658863408802356.208164155
#Sta/Elev= 30
9581.78937.063989695.064 35.07129706.30435.432139829.93732.3504210122.1629.66741
 10448.130.8840110605.4630.5968810639.0529.7797210650.4130.5226110661.6533.36143
10682.8631.2244710704.7730.9989510751.5732.2008910762.8133.5365110774.0532.56473
10796.5333.1748310807.7731.94099   1081933.2976910852.7233.5489710863.9634.39454
 10875.233.8922510897.68 35.639710942.6436.2351210953.8837.3208110998.84 36.9883
11011.4537.7717711032.5537.4712211043.7938.3561211066.2736.2907311074.5237.12495
#Mann= 3 , 0 , 0
9581.789    0.04       09581.789    0.04       011074.52    0.04       0
#XS Ineff= 2 , 0
       0                               0
Bank Sta=9581.789,11074.52
Exp/Cntr=0.3,0.1

Type RM Length L Ch R = 1 ,9962.463,98.550500,98.550500,98.550500
XS GIS Cut Line= 3
925861.269974519802920.444275266925661.617196741802712.110941933
924563.526918963802143.534553044
#Sta/Elev= 30
  9507.334.427649528.69233.347889545.26833.397139611.79631.456499764.15328.71589
9790.96627.688689920.06225.781659983.48325.811979994.74425.3595710028.5325.88472
10062.3125.1112610501.4925.9228610524.01 25.220810550.7625.7781210569.0624.79785
10602.8426.0664810625.3624.6471110715.4525.8792210771.7528.8235510794.2829.20455
10805.5428.8721910828.0629.3640210861.8428.6531710895.62 29.319410906.8930.19642
10929.4129.8024510940.6730.5147910963.1929.7075910985.7130.5725711032.4229.94571
#Mann= 3 , 0 , 0
  9507.3    0.04       0  9507.3    0.04       011032.42    0.04       0
#XS Ineff= 2 , 0
       0                               0
Bank Sta=9507.3,11032.42
Exp/Cntr=0.3,0.1

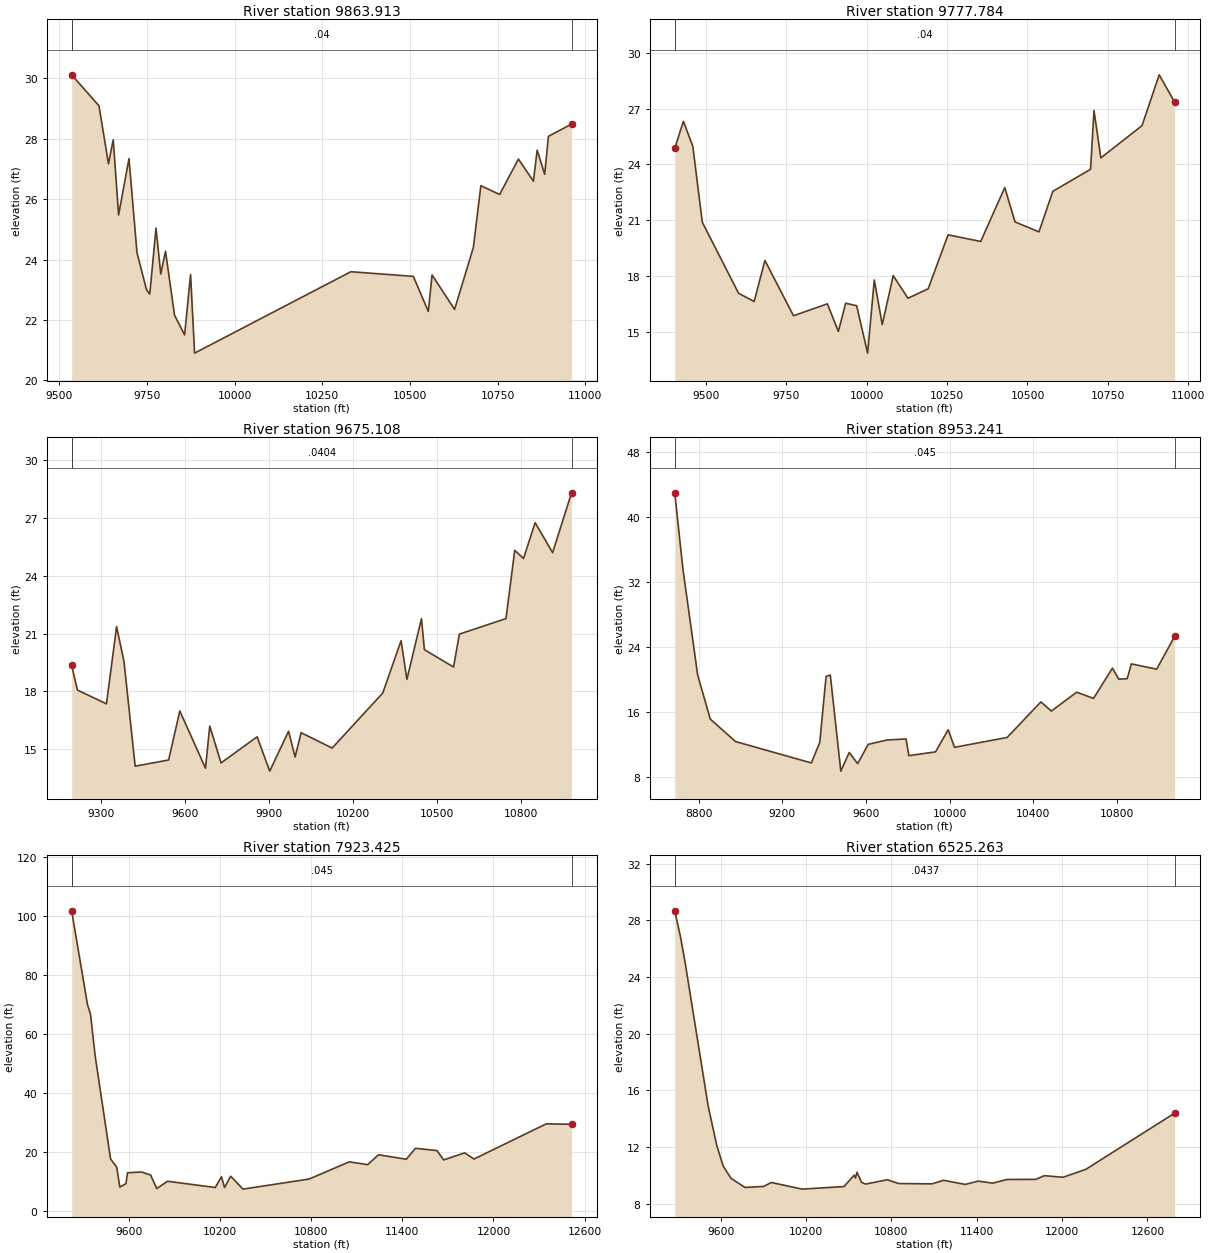
Type RM Length L Ch R = 1 ,9863.913,86.128100,86.128100,86.128100
XS GIS Cut Line= 4
925865.366005708802822.481148152925674.986386109802614.391796498
925130.412125397802313.326351552924643.394493867802127.374164967
#Sta/Elev= 30
 9535.4730.116789613.37829.091369640.48627.170579654.03927.966639669.34325.47939
9698.97227.341429721.80824.225699748.915 23.0019 9758.2322.854139776.02325.04006
9789.57623.52053 9803.13 24.27139828.91922.153999857.58821.504489874.62523.50402
9886.05120.9010210331.6823.5964810509.7823.44282 10552.622.28206 10563.323.48993
10627.5322.3489910681.0524.3993310702.4626.4461310755.9826.15437 10809.5 27.3272
10852.3126.5948810863.0227.6229410884.4326.8226510895.1328.0800310961.0728.48488
#Mann= 3 , 0 , 0
 9535.47    0.04       0 9535.47    0.04       010961.07    0.04       0
#XS Ineff= 2 , 0
       09878.754                       0
Bank Sta=9535.47,10961.07
Exp/Cntr=0.3,0.1

Type RM Length L Ch R = 1 ,9777.784,102.676400,102.676400,102.676400
XS GIS Cut Line= 4
926003.416735172802820.322749972925765.107176214802564.506044433
925247.677252293802283.382699907924670.083401889802066.850527748
#Sta/Elev= 30
9402.52224.862499429.54126.321899458.88324.968899488.22420.887339601.132 17.0625
9649.60316.618489683.13318.825569772.05415.84911 9877.4516.492749911.59215.00749
9934.35316.523659968.495 16.390310002.6413.8369110023.4217.7784310048.1615.37883
 10082.318.0098810128.1516.7937310190.9917.2995510253.0120.2073210354.5519.85212
 10429.322.7548310461.34 20.904210535.8120.3659410578.8222.5507910696.29 23.7375
10706.9726.9045210728.33 24.351810856.4926.0927910909.8928.8263510957.8627.35574
#Mann= 3 , 0 , 0
9402.522    0.04       09402.522    0.04       010957.86    0.04       0
#XS Ineff= 2 , 0
       09864.927                       0
Bank Sta=9402.522,10957.86
Exp/Cntr=0.3,0.1

Type RM Length L Ch R = 1 ,9675.108,721.866800,721.866800,721.866800
XS GIS Cut Line= 5
926177.027846307 802875.87830551926083.277846336802743.933861062
925862.315720439802491.457727611925279.627582669802194.929600537
924670.083401889802018.239416629
#Sta/Elev= 30
9195.55619.348539216.32218.070999319.91117.359339356.10721.361649382.57619.54343
9422.442 14.12919542.04214.450399581.90916.990699673.66714.024059688.85116.20509
9729.21414.296899858.221 15.65069903.10313.873069970.42515.938729993.79614.60818
10015.3115.8646710126.09 15.065910307.0417.9215210372.3720.6305410393.19 18.6245
10445.2521.7734210455.6620.1660510559.78 19.2659 10580.620.9718710747.1921.77628
10778.4225.3130110809.6624.88851 10851.326.7435910913.7725.1918610981.36 28.2911
#Mann= 3 , 0 , 0
9195.556  0.0404       09195.556  0.0404       010981.36  0.0404       0
#XS Ineff= 2 , 0
       09851.599                       0
Bank Sta=9195.556,10981.36
Exp/Cntr=0.3,0.1

Type RM Length L Ch R = 1 ,8953.241,1029.816400,1029.816400,1029.816400
XS GIS Cut Line= 2
 927003.79547773801791.019712602924629.663533285 801521.92249038
#Sta/Elev= 30
8685.99142.989258725.03533.604948795.48320.532198855.86715.096138976.63612.32735
9338.941 9.687119379.19712.223589409.38920.352719429.51720.522299479.8378.679507
9520.09310.972719560.3499.598845 9610.67 11.98089701.24612.520199791.822 12.6442
9804.92910.585749932.71911.056339993.10313.7775210023.2911.61468 10274.912.83257
10435.9217.2127710486.2416.0831510607.0118.4090210687.5217.64519 10778.121.37711
10808.2920.0140810848.5520.0748910868.6721.8966910989.44 21.250211075.3225.28434
#Mann= 3 , 0 , 0
8685.991   0.045       08685.991   0.045       011075.32   0.045       0
#XS Ineff= 2 , 0
       0 9743.17                       0
Bank Sta=8685.991,11075.32
Exp/Cntr=0.3,0.1

Type RM Length L Ch R = 1 ,7923.425,1398.162000,1398.162000,1398.162000
XS GIS Cut Line= 2
926547.736475488800488.067009838 923301.20869771801034.942009838
#Sta/Elev= 30
9221.918101.81079326.10270.074239346.38466.720929376.806 52.65099478.21517.79081
9518.77914.983029539.061 8.259089579.6249.4331869589.76513.104139681.03313.36347
9741.87812.339949782.4427.7517289853.42810.22185 10167.88.10812310208.3611.75282
10228.648.093588 10269.211.9321510350.337.56075610786.3910.9817611050.0516.79623
11171.7415.8531811242.7319.1993511425.2617.6815811486.1121.3888311628.0820.61436
11671.7117.4448711810.62 19.841911871.4617.7523812348.0929.6712512514.1829.52142
#Mann= 3 , 0 , 0
9221.918   0.045       09221.918   0.045       012514.18   0.045       0
#XS Ineff= 2 , 0
       0                               0
Bank Sta=9221.918,12514.18
Exp/Cntr=0.3,0.1

Type RM Length L Ch R = 1 ,6525.263,1080.155800,1080.155800,1080.155800
XS GIS Cut Line= 6
926352.383637238798882.065765766926131.011986543799050.308220295
925767.962479401 799214.12324181 925528.88109665799271.679870991
923837.601685334799550.608150868922960.969948578799515.188686756
#Sta/Elev= 30
9277.06128.671029314.963 26.96459349.13625.083289512.41914.871849572.77912.10599
 9616.9210.676499672.0969.8002699771.4149.1531249902.1999.2259829956.4939.504009
10172.499.03472110466.939.214575 10537.710.0167410547.849.82164410557.9710.22477
10590.479.50709110618.779.38972910770.789.69572510851.979.428745 11085.49.407406
11166.59  9.655711318.839.36774311410.179.60099111511.679.45450511612.91  9.7182
 11815.19.72303111875.299.98406412006.249.87154212166.3710.4292112790.9114.39456
#Mann= 3 , 0 , 0
9277.061  0.0437       09277.061  0.0437       012790.91  0.0437       0
#XS Ineff= 2 , 0
       0                10508.24       0
Bank Sta=9277.061,12790.91
Exp/Cntr=0.3,0.1

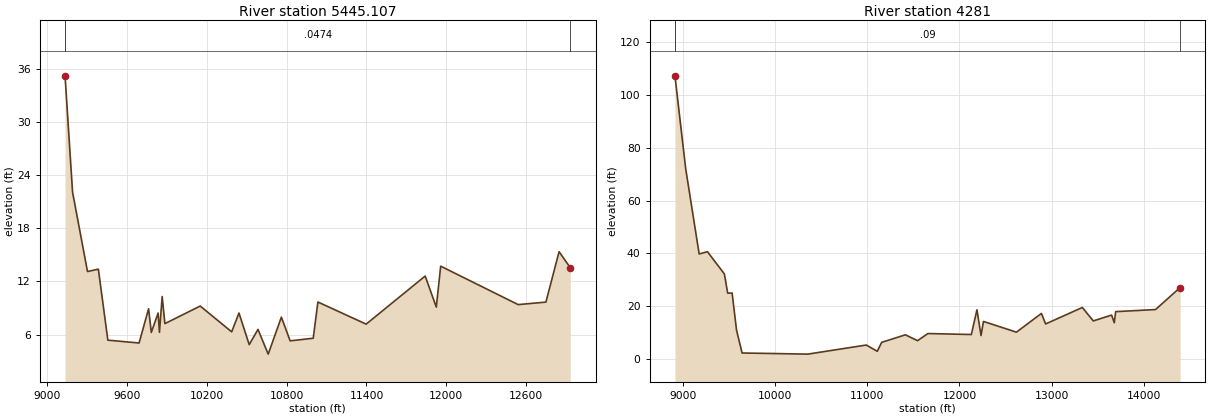
Type RM Length L Ch R = 1 ,5445.107,1164.107000,1164.107000,1164.107000
XS GIS Cut Line= 3
926250.273714553798019.144688232925048.884825664798269.144688232
922708.607047886799338.589132677
#Sta/Elev= 30
9132.49735.174369188.95522.070979301.31113.115069383.02513.384469454.5255.381496
9689.4525.0594619760.9518.919798 9781.386.2534699832.4518.4344599842.6656.268484
9863.093 10.29829883.5227.24416310149.099.22623710385.886.32068910440.868.436916
10517.82 4.8763110583.79 6.5936510660.753.807348 10759.77.97662810825.675.302928
10999.265.59968611034.579.68068911397.39 7.1861911841.3512.6061611925.139.111298
11958.1213.7204812540.849.38838312749.739.67189512848.6915.3523212932.6813.55578
#Mann= 3 , 0 , 0
9132.497  0.0474       09132.497  0.0474       012932.68  0.0474       0
#XS Ineff= 2 , 0
       0                10151.13       0
Bank Sta=9132.497,12932.68
Exp/Cntr=0.3,0.1

Type RM Length L Ch R = 1 ,    4281,0.000000,0.000000,0.000000
XS GIS Cut Line= 6
925721.581293864796598.927720308925115.642710412797003.594810484
924905.210917014797166.680189174924770.392604744797291.718468309
924559.455068038 797462.20829214921513.389854227800115.074388311
#Sta/Elev= 30
8908.491107.11359024.62972.157739171.507 39.79249261.53740.660599445.50432.25583
9481.57925.008019529.67925.029479577.77910.986049637.9292.38024210351.61 1.95077
10987.795.38907411107.14  3.010711154.646.40243711412.149.24854311544.757.033346
11657.119.72701512129.139.36157712190.0318.7052912234.318.98883112260.8314.30498
12618.8710.2510712890.4417.3240412936.1213.3527313334.9619.5770913453.8214.49784
13653.2216.6982313682.2113.8142213697.4418.0043714130.6118.7968514397.9627.12078
#Mann= 3 , 0 , 0
8908.491    0.09       08908.491    0.09       014397.96    0.09       0
#XS Ineff= 2 , 0
       0                10235.73       0
Bank Sta=8908.491,14397.96
Exp/Cntr=0.3,0.1